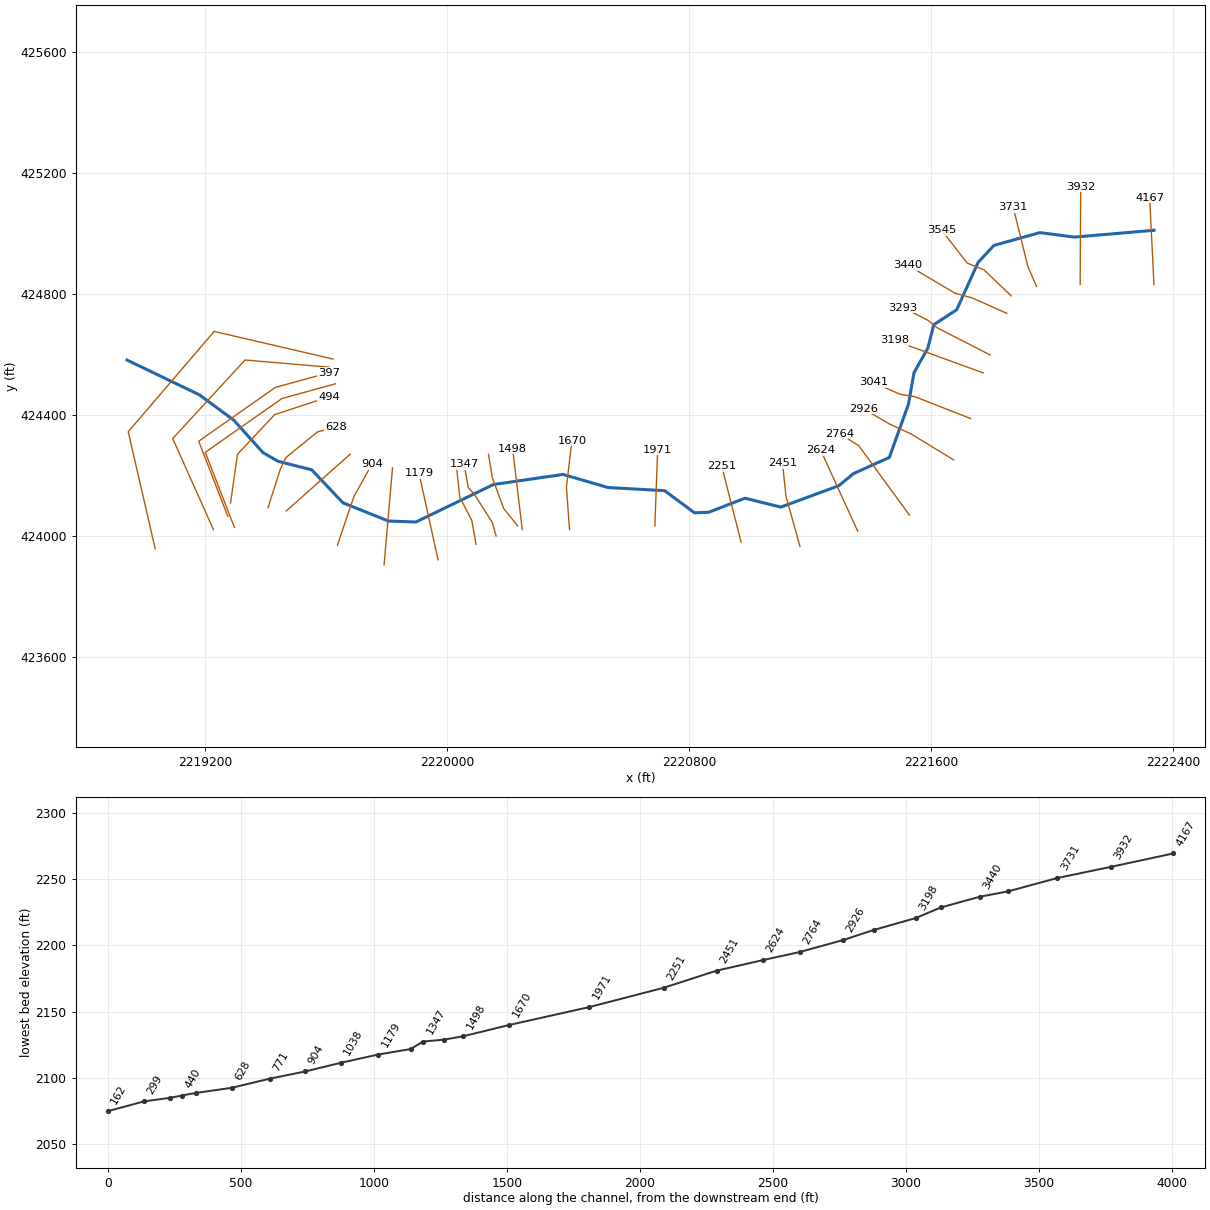
--- IMPRVMNTLKRN.prj (project) ---

Proj Title=IMPRVMNTLKRN
Current Plan=p01
Default Exp/Contr=0,0
English Units
Geom File=g01
Flow File=f01
Plan File=p01
Background Map Layer=Inundation Boundary (01pct Value_0)
BEGIN DESCRIPTION:
----------MODEL BY WOOD PLC 2021----------
Stream Name: Improvement Lick Run
Flood Zone: Enhanced Approximate
Pocahontas County, WV
HEC-RAS Version: RAS 6.1
Vertical Datum: NAVD88
Projection: NAD 1983 StatePlane West Virginia S FIPS 4702 (US Feet)
Terrain: 1-meter LIDAR (FEMA Region III 3DEP collected 2016-2018)
Land Use: 2019 NLCD
Hydrologic Method:
WV SIR2010-5033 regression equations
Model Notes:
Normal depth tie in to Greenbrier River.
END DESCRIPTION:
DSS Export Rating Curves= 0
DSS Export Rating Curve Sorted= 0
DSS Export Volume Flow Curves= 0
DXF OffsetX= 0
DXF OffsetY= 0
DXF ScaleX= 0
DXF ScaleY= 0

--- IMPRVMNTLKRN.p01 (plan) ---

Plan Title=Floodplain
Program Version=6.10
Short Identifier=Floodplain
Geom File=g01
Flow File=f01
Subcritical Flow
K Sum by GR= 0
Std Step Tol= 0.01
Critical Tol= 0.01
Num of Std Step Trials= 20
Max Error Tol= 0.3
Flow Tol Ratio= 0.001
Split Flow NTrial= 30
Split Flow Tol= 0.02
Split Flow Ratio= 0.02
Log Output Level= 0
Friction Slope Method= 1
Unsteady Friction Slope Method= 2
Unsteady Bridges Friction Slope Method= 1
Parabolic Critical Depth
Global Vel Dist= 0 , 0 , 0
Global Log Level= 0
CheckData=True
Encroach Param=-1 ,0,0, 0
Mapping Interval=1HOUR
Computation Time Step Use Courant=        0
Computation Time Step Use Time Series=    0
Computation Time Step Count To Double=0
Computation Time Step Max Doubling=0
Computation Time Step Max Halving=0
Computation Time Step Residence Courant=0
Run HTab= 0
Run UNet= 0
Run Sediment= 0
Run PostProcess= 0
Run WQNet= 0
Run RASMapper=-1
UNET Theta= 0
UNET Theta Warmup= 0
UNET ZTol= 0
UNET ZSATol= 0
UNET MxIter= 0
UNET Max Iter WO Improvement= 0
UNET MaxInSteps= 0
UNET DtIC= 0
UNET DtMin= 0
UNET MaxCRTS= 0
UNET WFStab= 0
UNET SFStab= 0
UNET WFX= 1
UNET SFX= 1
UNET Gravity=32.174
UNET 1D Methodology=Finite Difference
UNET DSS MLevel= 1
UNET Pardiso=0
UNET DZMax Abort= 0
UNET Use Existing IB Tables= 0
UNET Froude Reduction=False
UNET Froude Limit= 0
UNET Froude Power= 0
UNET D1 Cores= 0
UNET WindReference=Eulerian
UNET WindDragFormulation=Hsu (1988)
UNET D2 Coriolis=0
UNET D2 Cores= 0
UNET D2 Theta= 1
UNET D2 Theta Warmup= 1
UNET D2 Z Tol= 0.01
UNET D2 Volume Tol= 0.01
UNET D2 Max Iterations= 20
UNET D2 Equation= 0
UNET D2 RampUpFraction=0.1
UNET D2 TimeSlices= 1
UNET D2 Turbulence Formulation=Non-Conservative (original)
UNET D2 Eddy Viscosity=0.3
UNET D2 Transverse Eddy Viscosity=0.1
UNET D2 Smagorinsky Mixing=0
UNET D2 BCVolumeCheck=0
UNET D2 Cores=0
UNET D2 SolverType=PARDISO (Direct)
UNET D2 Minimum Iterations= 2147483647
UNET D2 Maximum Iterations= 2147483647
UNET D2 Restart Number= 10
UNET D2 Relaxation Coeff=1.3
UNET D2 SOR Precondition Iterations= 10
UNET D2 ILUT Maximum Fill= 8
UNET D2 ILUT Tolerance=1E-08
UNET D1D2 MaxIter= 0
UNET D1D2 ZTol=0.01
UNET D1D2 QTol=0.1
UNET D1D2 MinQTol=1
Write IC File= 0
Write IC File at Fixed DateTime=0
Write IC File at Sim End=0
Echo Input=False
Echo Parameters=False
Echo Output=False
Write Detailed= 0
HDF Write Warmup=0
HDF Write Time Slices=0
HDF Flush=0
HDF Compression= 1
HDF Chunk Size= 1
HDF Spatial Parts= 1
HDF Use Max Rows=0
HDF Fixed Rows= 1
Calibration Method= 0
Calibration Iterations= 20
Calibration Max Change=0.05
Calibration Tolerance=0.2
Calibration Maximum=1.5
Calibration Minimum=0.5
Calibration Optimization Method= 1
WQ AD Non Conservative
WQ ULTIMATE=-1
WQ Max Comp Step=1HOUR
WQ Output Interval=15MIN
WQ Output Selected Increments= 0
WQ Output face flow=0
WQ Output face velocity=0
WQ Output face area=0
WQ Output face dispersion=0
WQ Output cell volume=0
WQ Output cell surface area=0
WQ Output cell continuity=0
WQ Output cumulative cell continuity=0
WQ Output face conc=0
WQ Output face dconc_dx=0
WQ Output face courant=0
WQ Output face peclet=0
WQ Output face adv mass=0
WQ Output face disp mass=0
WQ Output cell mass=0
WQ Output cell source sink temp=0
WQ Output nsm pathways=0
WQ Output nsm derived pathways=0
WQ Create Restart=0
WQ Fixed Restart=0
WQ System Summary=0
WQ Write To DSS=0
Sorting and Armoring Iterations= 10
XS Update Threshold= 0.02
Bed Roughness Predictor= 0
Hydraulics Update Threshold= 0.02
Energy Slope Method= 1
Volume Change Method= 1
Sediment Retention Method= 0
Sediment TS Multiplier= 1
Warm Up Method= 0
XS Weighting Method= 0
Number of US Weighted Cross Sections= 1
Number of DS Weighted Cross Sections= 1
Upstream XS Weight=0
Main XS Weight=1
Downstream XS Weight=0
Number of DS XS's Weighted with US Boundary= 1
Upstream Boundary Weight= 1
Weight of XSs Associated with US Boundary= 0
Number of US XS's Weighted with DS Boundary= 1
Downstream Boundary Weight= 0.5
Weight of XSs Associated with DS Boundary= 0.5
Percentile Method= 0
Sediment Output Level= 3
Mass or Volume Output= 0
Output Increment Type= 1
Profile and TS Output Increment= 1
Transport Output Increment 1
XS Output Flag= 0
XS Output Increment= 10
Read HDF5 Sediment Hotstart= 0
Sediment Hotstart Type= 0
Write Gradation File= 0
Read Gradation Hotstart= 0
Write HDF5 File= 1
Write Binary Output= 1
Write DSS Sediment File= 0
DSS Sediment Output Type= 1
SV Curve= 0
Specific Gage Flag= 0
Subcell Erosion Methods= 0
Subcell Deposition Methods= 0
Advection Scheme= 1
Matrix Solver= 0
Implicit Weighting Factor= 1
Maximum Outer Loop Convergence Iterations= 5
Convergence Maximum Absolute= 0.001
Convergence RMSE= 0.0001
Grain Fractions Max Abs Error= 0.001
Max Subgrid Regions= 1
Max Subgrid Length Scale= 3.402823E+38
Initial Layer Thickness= 3.402823E+38
Min Layer Thickness= 3.402823E+38
Max Layer Thickness= 3.402823E+38
Number of Layers= 5

--- IMPRVMNTLKRN.f01 (steady flow) ---

Flow Title=Flow
Program Version=6.10
Number of Profiles= 6
Profile Names=01pct,10pct,04pct,02pct,0_2pct,01plus
River Rch & RM=IMPRVMNTLKRN,Main,4167
     681     362     480     577     948    1010
Boundary for River Rch & Prof#=IMPRVMNTLKRN,Main            , 1
Up Type= 0
Dn Type= 3
Dn Slope=0.03179
Boundary for River Rch & Prof#=IMPRVMNTLKRN,Main            , 2
Up Type= 0
Dn Type= 3
Dn Slope=0.03179
Boundary for River Rch & Prof#=IMPRVMNTLKRN,Main            , 3
Up Type= 0
Dn Type= 3
Dn Slope=0.03179
Boundary for River Rch & Prof#=IMPRVMNTLKRN,Main            , 4
Up Type= 0
Dn Type= 3
Dn Slope=0.03179
Boundary for River Rch & Prof#=IMPRVMNTLKRN,Main            , 5
Up Type= 0
Dn Type= 3
Dn Slope=0.03179
Boundary for River Rch & Prof#=IMPRVMNTLKRN,Main            , 6
Up Type= 0
Dn Type= 3
Dn Slope=0.03179
DSS Import GetInterval= 0
DSS Import GetPeak= 0
DSS Import FillOption= 0

--- IMPRVMNTLKRN.g01 (geometry) ---

Geom Title=Geometry
Program Version=6.10

River Reach=IMPRVMNTLKRN    ,Main
Reach XY= 30
     2222336.307      425010.773     2222072.849      424988.271
     2221958.801      425003.0712221806.77656147424960.801287391
2221754.63837769424904.652474091     2221683.804      424748.042
2221607.97631139424698.4738877742221588.08312373424620.322079113
2221542.61298051424540.038857489     2221524.374      424435.769
2221460.94682565424259.323876077     2221342.073      424205.742
2221294.29313715424166.056285494     2221102.218       424095.07
     2220983.782      424124.603     2220863.559      424078.008
     2220816.764      424076.338     2220718.401      424149.443
2220530.61954447 424159.92603827     2220382.505      424203.208
     2220152.111      424169.881 2219895.8736537424045.899830348
     2219805.145      424049.073     2219654.799      424109.169
     2219551.132      424218.625     2219439.704      424246.753
     2219390.214      424275.365        2219294.      424382.343
     2219179.569      424466.753     2218940.644      424581.586

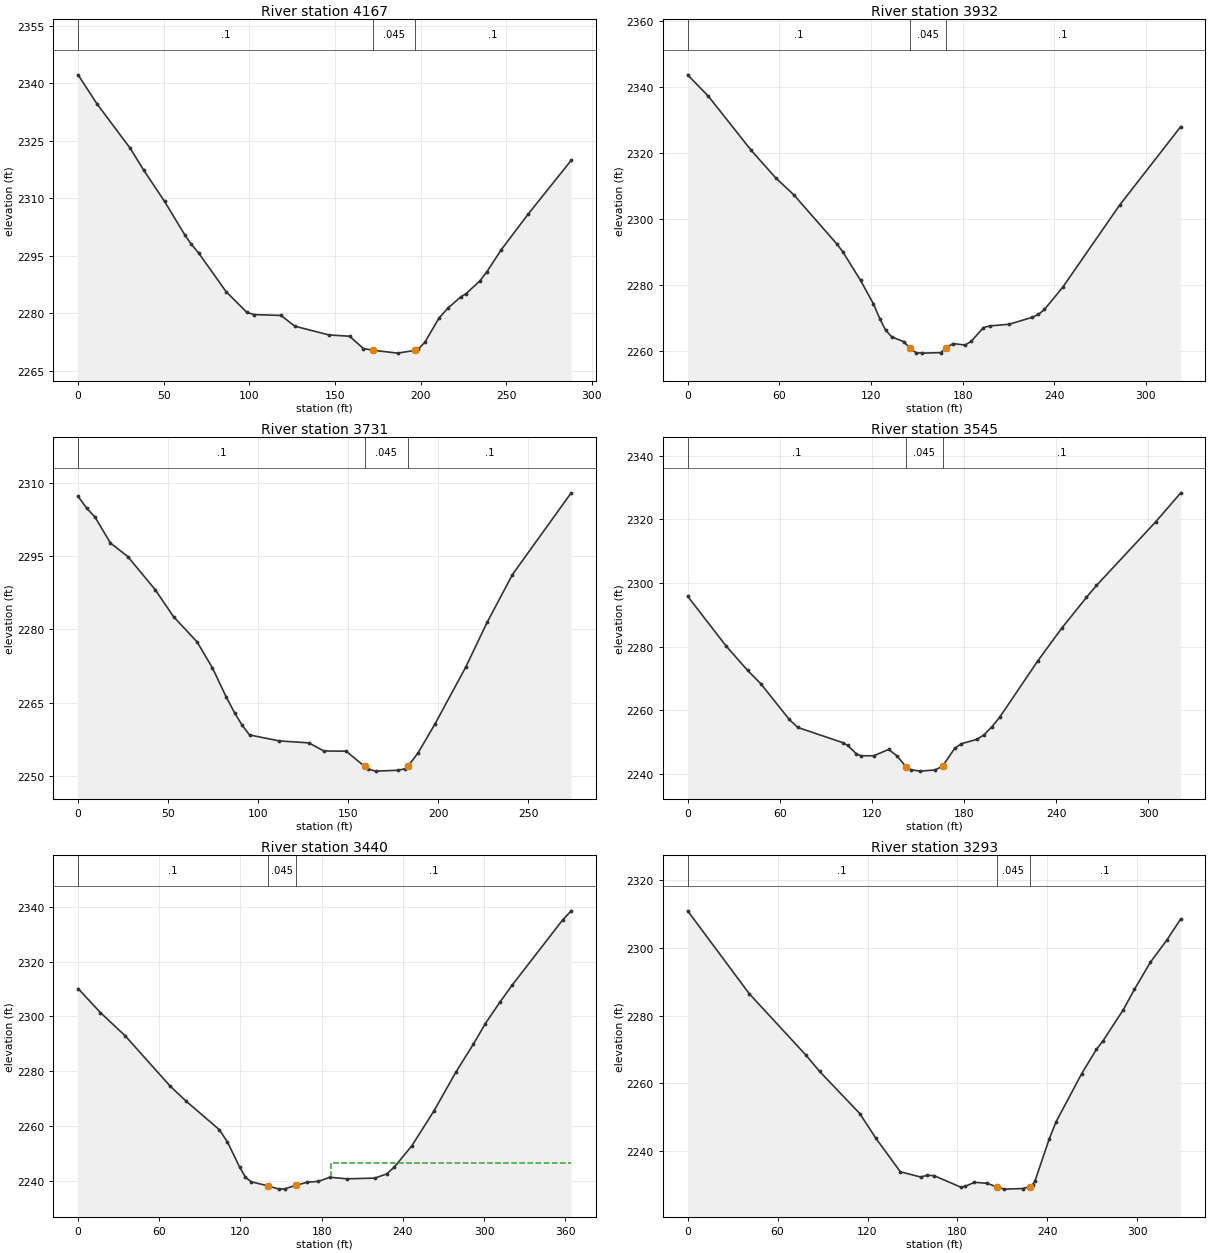
Type RM Length L Ch R = 1 ,4167    ,235.2,235.2,235.2
XS GIS Cut Line= 2
2222335.99729442424830.7795298852222321.74240339425118.392919359
#Sta/Elev= 30
       0 2342.22    11.1 2334.61    30.4 2323.08    38.4  2317.3    50.5  2309.2
    62.5 2300.33    65.9 2298.14    70.5 2295.67    86.5 2285.61    98.5 2280.26
   102.5 2279.66   118.5 2279.42   126.6 2276.62   146.6 2274.33   158.6    2274
   166.6 2270.79  172.462270.334   186.6 2269.59   196.7  2270.3   198.6 2270.58
   202.6 2272.47   210.7 2278.68   215.8 2281.24   223.4 2284.24   226.7 2285.14
   234.7 2288.46   238.7 2290.78   247.1 2296.54   262.7 2305.78     288  2319.9
#Mann= 3 ,-1,0
       0      .1       0  172.46    .045       0   196.7      .1       0
Bank Sta=172.46,196.7
XS Rating Curve= 0 ,0
Exp/Cntr(USF)=0,0
Exp/Cntr=0.3,0.1

Type RM Length L Ch R = 1 ,3932    ,195.4,201.3,204.8
XS GIS Cut Line= 2
2222091.98710101424831.6180528862222093.66414702425154.449408418
#Sta/Elev= 30
       0 2343.74    13.6 2337.24    41.6 2320.87    57.6 2312.54    69.6 2307.34
    97.6 2292.53   101.6 2290.09   113.2 2281.45   121.6 2274.34     126 2269.64
   129.6 2266.37   133.6 2264.34   141.6 2262.86   145.6 2260.88   149.6 2259.52
   153.6 2259.41   165.6 2259.56   168.9 2260.86   173.6 2262.31   181.6 2261.86
   185.6 2262.97   193.6 2267.13   197.6 2267.65   210.5 2268.16   225.6 2270.27
   229.6 2271.13   233.6 2272.64   245.6 2279.42   282.8 2304.27   322.8 2328.05
#Mann= 3 ,-1,0
       0      .1       0   145.6    .045       0   168.9      .1       0
Bank Sta=145.6,168.9
XS Rating Curve= 0 ,0
Exp/Cntr(USF)=0,0
Exp/Cntr=0.3,0.1

Type RM Length L Ch R = 1 ,3731    ,168,185.7,201.2
XS GIS Cut Line= 3
2221948.01270168424824.6583119752221919.25136273424890.314662983
2221870.61702865425086.529045306
#Sta/Elev= 30
       0 2307.19     4.9 2304.72     9.4 2302.94      18 2297.63    27.6 2294.88
    42.8 2288.11      53 2282.59    66.1 2277.41    74.6 2272.11    82.3 2266.11
      87 2262.86    91.1 2260.38    95.2 2258.39   111.7 2257.17   128.2 2256.77
   136.4 2255.11   148.8 2255.07   159.1 2251.97   159.1 2251.95   161.2 2251.39
   165.3 2250.99   177.7 2251.17   181.8  2251.5  183.172251.985   188.9 2254.79
   198.3 2260.72   215.3  2272.3   227.1  2281.4   241.2  2291.2   273.8 2307.91
#Mann= 3 ,-1,0
       0      .1       0   159.1    .045       0  183.17      .1       0
Bank Sta=159.1,183.17
XS Rating Curve= 0 ,0
Exp/Cntr(USF)=0,0
Exp/Cntr=0.3,0.1

Type RM Length L Ch R = 1 ,3545    ,103.4,105.2,106.7
XS GIS Cut Line= 4
2221864.07643835424793.805955499 2221773.5159542424880.173824642
2221719.01195911424901.9754226782221634.32113597425010.144889857
#Sta/Elev= 30
       0 2295.82    24.9 2280.27    39.1 2272.49    47.6 2268.36    66.2  2257.1
    71.7  2254.6   101.3 2249.77   104.2 2248.94   109.8 2246.35   112.7  2245.7
   121.1 2245.68   130.9 2247.67   136.2 2245.72   142.3 2242.24   145.4 2241.27
   151.6 2240.86   161.1 2241.23  166.032242.392     174 2248.05   178.3 2249.48
   188.4 2250.84     193 2252.26   198.1 2254.76   203.2 2257.75     228 2275.45
   243.8 2285.85   259.8 2295.48   266.3  2299.2   304.8 2319.16   321.2 2328.31
#Mann= 3 ,-1,0
       0      .1       0   142.3    .045       0  166.03      .1       0
Bank Sta=142.3,166.03
XS Rating Curve= 0 ,0
Exp/Cntr(USF)=0,0
Exp/Cntr=0.3,0.1

Type RM Length L Ch R = 1 ,3440    ,153.5,146.9,141
XS GIS Cut Line= 4
2221849.06698751 424736.277987632221734.86015472424787.092481513
2221678.42755673424802.6051570382221522.79768768424894.674982589
#Sta/Elev= 30
       0 2310.22    16.5 2301.43    34.7 2292.99      68 2274.55    79.8 2269.05
   104.4 2258.58   110.4  2254.1   119.5 2244.79   123.6 2241.29   127.8 2239.56
   140.12238.073   148.5 2236.85   152.7 2236.94     161 2238.25   169.3 2239.36
   177.6 2239.69   186.1 2241.19   198.7 2240.62   219.2 2240.88     228 2242.39
   233.8 2244.98   246.6 2252.68     263 2265.46   279.1 2279.58   292.2 2289.94
   300.9 2297.35   311.6 2305.14   320.9 2311.54   358.1 2335.32   364.4 2338.64
#Mann= 3 ,-1,0
       0      .1       0   140.1    .045       0     161      .1       0
#XS Ineff= 2 , 0
                          187.04         2246.46
Permanent Ineff=
       F       F
Bank Sta=140.1,161
XS Rating Curve= 0 ,0
Exp/Cntr(USF)=0,0
Exp/Cntr=0.3,0.1

Type RM Length L Ch R = 1 ,3293    ,91.6,95,101.5
XS GIS Cut Line= 4
2221794.47902923424598.4300961762221620.90476795424687.313534323
2221588.20237089424713.3077473662221506.02711676424755.233897435
#Sta/Elev= 30
       0 2310.94    41.1 2286.46      79 2268.28      88 2263.53   114.9 2251.03
   125.6 2243.75   141.9 2233.86   155.4 2232.31   159.9 2232.81   164.4 2232.71
   182.3  2229.3     185 2229.52   191.3 2230.74   199.7 2230.46   206.2  2229.4
   211.3 2228.73   223.7  2228.9   228.2 2229.47   230.1 2230.08   231.7 2231.09
   241.3 2243.62   245.8 2248.62   262.9 2262.84   272.7    2270   277.2 2272.58
   290.7 2281.75   298.1 2287.75   308.7 2295.72   319.7  2302.3     329 2308.56
#Mann= 3 ,-1,0
       0      .1       0   206.2    .045       0   228.2      .1       0
Bank Sta=206.2,228.2
XS Rating Curve= 0 ,0
Exp/Cntr(USF)=0,0
Exp/Cntr=0.3,0.1

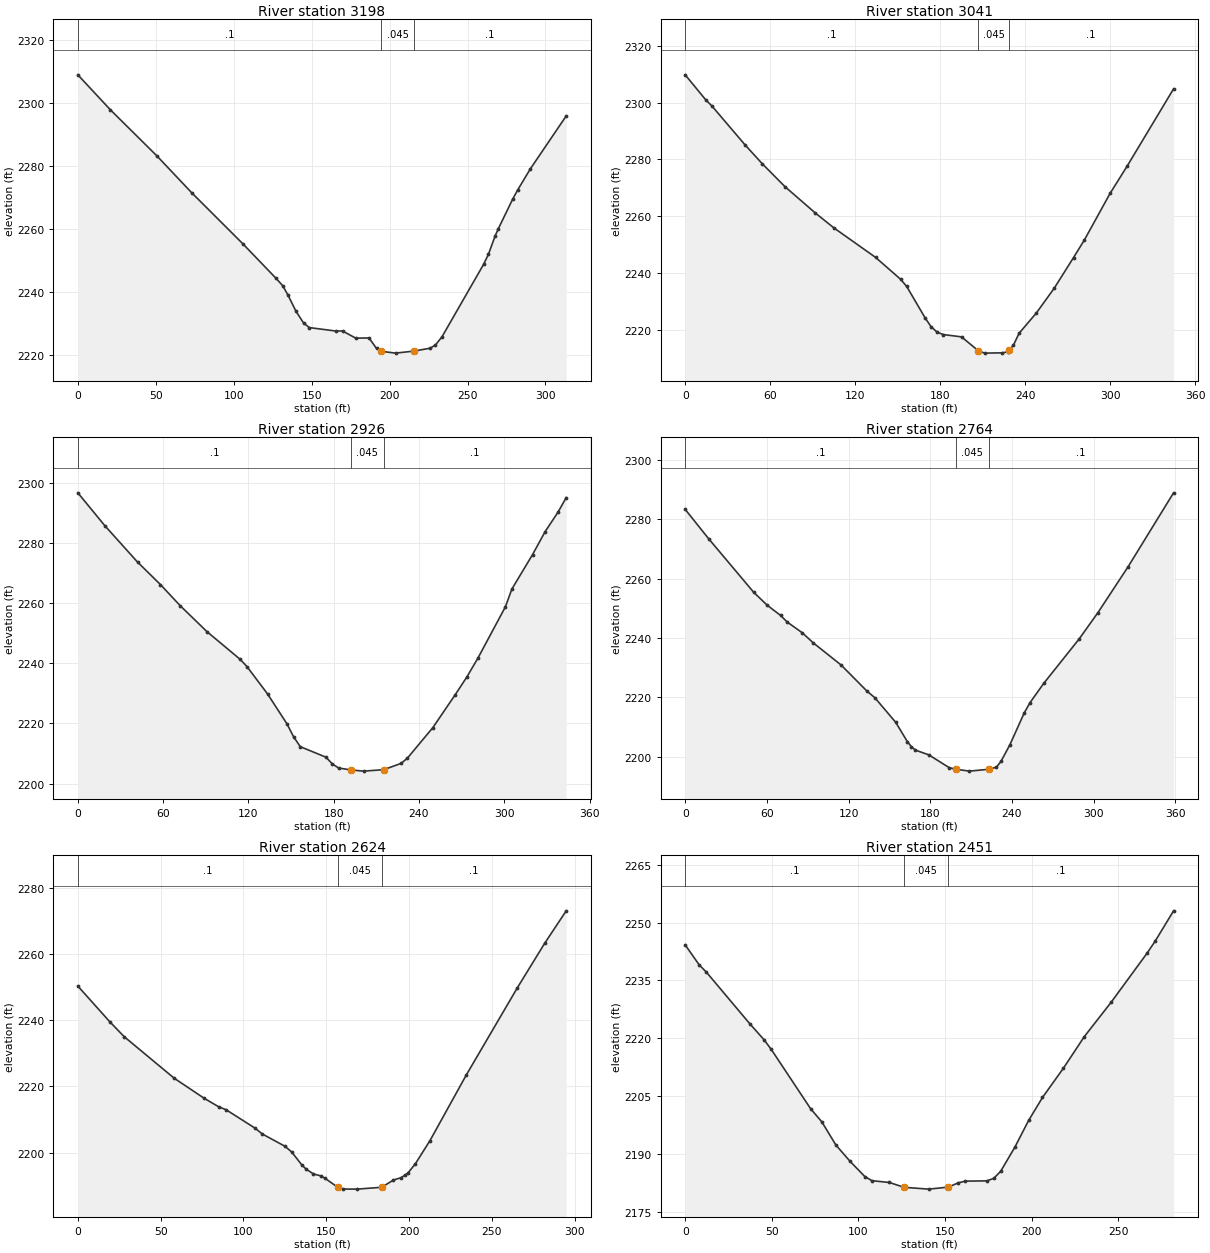
Type RM Length L Ch R = 1 ,3198    ,155,157.3,160.5
XS GIS Cut Line= 2
2221771.67131449424538.973525403  2221477.349741 424646.30446958
#Sta/Elev= 30
       0 2308.82    20.8 2297.78    50.6  2283.2    73.1 2271.44   105.9 2255.27
   127.2 2244.33   131.5 2241.97   134.9 2238.96     140 2233.87   144.8 2230.22
   148.5 2228.75   165.5 2227.66   169.8 2227.68   178.3  2225.4   186.8 2225.47
   191.6 2222.15   194.8 2221.23   203.8 2220.66   215.52221.302     226 2222.22
   229.4 2223.23   233.6 2225.82   260.3 2248.78   263.4 2251.97   267.7 2257.77
   269.6 2259.92     279 2269.48   282.1 2272.29   290.3 2279.04   313.3  2295.8
#Mann= 3 ,-1,0
       0      .1       0   194.8    .045       0   215.5      .1       0
Bank Sta=194.8,215.5
XS Rating Curve= 0 ,0
Exp/Cntr(USF)=0,0
Exp/Cntr=0.3,0.1

Type RM Length L Ch R = 1 ,3041    ,120,114.4,108.9
XS GIS Cut Line= 4
2221729.74516441424388.0393851552221546.27622083424460.073800947
2221495.96484075424468.4590309612221407.75233189424507.948174353
#Sta/Elev= 30
       0  2309.8    14.6 2300.93    18.9  2298.8    42.2 2285.14    54.5 2278.41
    70.4  2270.4    91.9 2261.08   104.8 2255.91   134.5 2245.41   152.1 2237.72
   156.4 2235.19   169.3 2224.18   173.6 2221.01   177.9 2219.05   182.2 2218.24
   195.1 2217.42   206.8 2212.59   211.4 2211.69   223.6 2211.79   227.6 2212.11
  228.542212.627   231.7 2214.45   235.7 2218.67   247.9 2225.82   260.6 2234.62
   274.2  2245.4   281.8 2251.55     300 2268.02   312.1 2277.68   344.8 2304.86
#Mann= 3 ,-1,0
       0      .1       0   206.8    .045       0  228.54      .1       0
Bank Sta=206.8,228.54
XS Rating Curve= 0 ,0
Exp/Cntr(USF)=0,0
Exp/Cntr=0.3,0.1

Type RM Length L Ch R = 1 ,2926    ,171.2,162.7,149.7
XS GIS Cut Line= 4
2221673.73171703424251.281573601 2221533.6983758424336.810919743
2221462.42392069424369.5133167972221375.21752854424420.663219882
#Sta/Elev= 30
       0 2296.74      19  2285.8      42  2273.7    58.1 2266.22    72.1 2259.14
    90.9 2250.52   114.3 2241.28     119 2238.91   133.5 2229.79   147.1 2219.88
   151.8 2215.55   156.5 2212.26   174.6 2208.75     179 2206.55   183.4 2205.17
   192.2 2204.51     201 2204.12   215.2  2204.6   227.4 2206.69   231.9 2208.46
   249.8 2218.62   265.6 2229.61   273.5  2235.3   281.4 2241.66   300.8 2258.79
   305.4 2264.74   319.9 2276.17   328.8 2283.85   337.9 2290.36   343.6 2295.15
#Mann= 3 ,-1,0
       0      .1       0   192.2    .045       0   215.2      .1       0
Bank Sta=192.2,215.2
XS Rating Curve= 0 ,0
Exp/Cntr(USF)=0,0
Exp/Cntr=0.3,0.1

Type RM Length L Ch R = 1 ,2764    ,141.8,139.4,133.1
XS GIS Cut Line= 3
2221527.66112108424068.5621216292221359.95652081424298.317424008
 2221297.0672957424337.728005072
#Sta/Elev= 30
       0 2283.32    17.2 2273.44    50.3 2255.38    60.2 2251.03    70.1 2247.55
      75 2245.32      86 2241.72    94.1 2238.31   114.5 2230.86   133.5 2222.06
   139.4 2219.78   154.7 2211.48   163.2    2205   166.1 2203.35   169.1 2202.16
     179 2200.55   193.9 2196.25   198.9  2195.7   208.8 2195.08     223  2195.7
   228.6 2196.41     232 2198.41   238.5 2203.99   249.1 2214.78   253.3 2218.19
   263.4  2224.7   289.3 2239.61   303.1 2248.48   325.3 2263.98   358.7  2288.9
#Mann= 3 ,-1,0
       0      .1       0   198.9    .045       0     223      .1       0
Bank Sta=198.9,223
XS Rating Curve= 0 ,0
Exp/Cntr(USF)=0,0
Exp/Cntr=0.3,0.1

Type RM Length L Ch R = 1 ,2624    ,176.8,173.6,170.6
XS GIS Cut Line= 2
 2221356.3508719424015.735172542 2221233.9265137424284.062532984
#Sta/Elev= 30
       0  2250.4    19.2 2239.65      28 2235.07    58.2 2222.49    76.3 2216.42
    85.1 2213.83    89.5 2212.96   106.9 2207.41   111.5 2205.58     125 2201.91
   129.1 2200.18   135.3 2196.21   137.9 2194.95   142.3  2193.5   146.7 2192.93
   149.2 2192.21  157.072189.424   159.9 2188.93   168.7 2188.91   183.5 2189.47
   190.6 2191.68     195 2192.35   197.5  2193.1   199.4 2193.83   203.8 2196.58
   212.6 2203.57   234.6 2223.51   265.4 2249.89     282 2263.44   294.9 2273.19
#Mann= 3 ,-1,0
       0      .1       0  157.07    .045       0   183.5      .1       0
Bank Sta=157.07,183.5
XS Rating Curve= 0 ,0
Exp/Cntr(USF)=0,0
Exp/Cntr=0.3,0.1

Type RM Length L Ch R = 1 ,2451    ,203.6,199.6,196.6
XS GIS Cut Line= 3
2221165.58677819423965.3452301292221119.46801312424130.534261402
 2221107.7286911424240.380774583
#Sta/Elev= 30
       0 2244.21     8.1 2239.03    12.3 2237.12    37.2 2223.84    45.5 2219.66
    49.7 2217.14    72.4  2201.8    78.9 2198.38      87 2192.39    95.2 2188.16
   103.7 2184.23   107.8 2183.15   117.9 2182.68  126.352181.432   140.6 2180.96
  151.932181.482   157.6 2182.58   161.8 2183.03   174.2  2183.1   178.2 2183.76
   182.2  2185.6   190.3 2191.78   198.3 2198.74   206.3 2204.69   218.4 2212.28
   230.5 2220.48     246 2229.38   266.7 2242.06   271.4  2245.2     282 2253.03
#Mann= 3 ,-1,0
       0      .1       0  126.35    .045       0  151.93      .1       0
Bank Sta=126.35,151.93
XS Rating Curve= 0 ,0
Exp/Cntr(USF)=0,0
Exp/Cntr=0.3,0.1

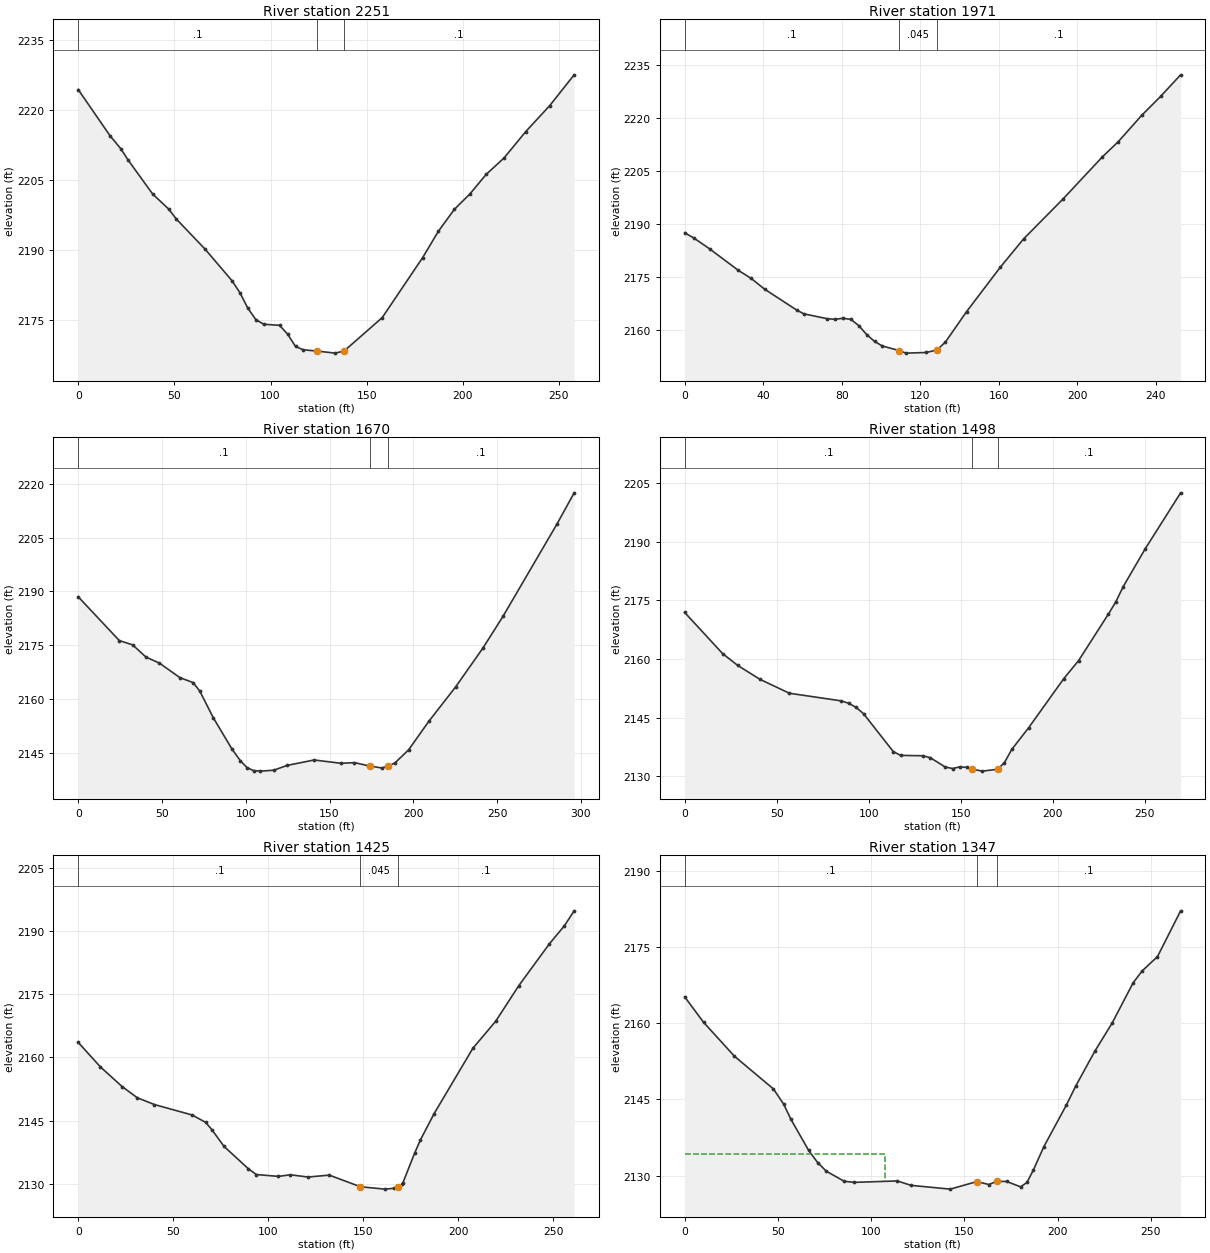
Type RM Length L Ch R = 1 ,2251    ,280.8,279.6,275.3
XS GIS Cut Line= 2
2220970.88184817423979.6786834822220907.15410006424229.558537894
#Sta/Elev= 30
       0 2224.47    16.6 2214.54    22.2 2211.76      26 2209.33    38.7 2202.09
      47 2198.87    51.1 2196.69      66 2190.25      80 2183.48    84.1 2180.91
    88.2 2177.61    92.4 2175.14    96.5 2174.16   104.7 2173.93   108.9 2172.04
     113  2169.4   117.1 2168.68   124.3 2168.41   133.6 2167.97   138.3 2168.43
   158.1 2175.59   179.1 2188.44   187.3 2194.09   195.6 2198.79   203.8 2202.14
   212.1 2206.27   221.4 2209.79   232.7 2215.45   245.1 2220.98   257.9 2227.63
#Mann= 3 ,-1,0
       0      .1       0   124.3    .045       0   138.3      .1       0
Bank Sta=124.3,138.3
XS Rating Curve= 0 ,0
Exp/Cntr(USF)=0,0
Exp/Cntr=0.3,0.1

Type RM Length L Ch R = 1 ,1971    ,302.7,301.6,300
XS GIS Cut Line= 2
 2220685.7840277424032.5056325692220695.00778071424284.901055985
#Sta/Elev= 30
       0 2187.53     4.7 2186.03    12.7 2182.97    27.3 2176.88    33.9 2174.57
    40.7 2171.54      57 2165.63    60.7 2164.54    72.7 2163.15    76.7 2162.99
    80.7 2163.29    84.7 2162.96    88.7 2161.19    92.7 2158.66    96.7 2156.72
   100.7 2155.42   109.22154.137   112.7  2153.4   122.9 2153.58   128.42154.258
   132.8 2156.54   143.6 2165.18   160.8 2177.79   172.7 2185.84   192.8 2197.16
   212.8 2209.08   220.8 2213.33   232.8 2220.83   242.4 2226.19   252.6 2232.31
#Mann= 3 ,-1,0
       0      .1       0   109.2    .045       0   128.4      .1       0
Bank Sta=109.2,128.4
XS Rating Curve= 0 ,0
Exp/Cntr(USF)=0,0
Exp/Cntr=0.3,0.1

Type RM Length L Ch R = 1 ,1670    ,168.8,171.8,174.1
XS GIS Cut Line= 3
2220403.62103774 424020.766310552220393.47490942424161.218913282
2220411.58700624424315.339440935
#Sta/Elev= 30
       0 2188.51    24.5  2176.3    32.5 2175.08    40.5 2171.65    48.5 2169.99
    60.6 2165.96    68.6 2164.55    72.6 2162.15    80.6 2154.75    91.8 2145.97
    96.7 2142.79   100.7 2140.83   104.7 2139.97   108.7 2139.83   116.7 2140.08
   124.7 2141.43   140.8 2142.94   156.9 2142.02   164.9  2142.2   174.12141.242
   181.1 2140.72   185.1 2141.21   189.1 2142.15   197.2 2145.78   209.2  2153.7
   225.4 2163.44   241.5 2174.16   253.5 2183.03   285.8 2208.87     296 2217.54
#Mann= 3 ,-1,0
       0      .1       0   174.1    .045       0   185.1      .1       0
Bank Sta=174.1,185.1
XS Rating Curve= 0 ,0
Exp/Cntr(USF)=0,0
Exp/Cntr=0.3,0.1

Type RM Length L Ch R = 1 ,1498    ,69.8,72.8,75
XS GIS Cut Line= 2
2220247.40409168 424020.687748222220215.54021762424288.176585662
#Sta/Elev= 30
       0  2171.9    20.6 2161.39    28.7  2158.4    40.8 2154.83    56.9 2151.25
    85.1  2149.3    89.1 2148.69    93.1 2147.65    97.2 2146.01   113.3 2136.35
   117.3 2135.37   129.4 2135.28   133.4 2134.79   141.5 2132.41   145.5 2132.02
   149.5 2132.44   153.6 2132.29  155.98 2131.86   161.7 2131.35     1702131.827
   173.7 2133.53   177.7 2136.91   186.9 2142.47   205.9 2154.97     214 2159.61
   230.2 2171.51   234.1 2174.53   238.2 2178.49   250.2 2188.19   269.4 2202.47
#Mann= 3 ,0,0
       0      .1       0  155.98    .045       0     170      .1       0
Bank Sta=155.98,170
XS Rating Curve= 0 ,0
Exp/Cntr(USF)=0,0
Exp/Cntr=0.3,0.1

Type RM Length L Ch R = 1 ,1425    ,78,78,78
XS GIS Cut Line= 4
2220232.44395725424033.0217077042220185.91504158 424090.57062972
2220148.56946453424192.1995771092220135.71279046424269.951844088
#Sta/Elev= 30
       0 2163.58    11.7 2157.76    23.1 2153.11    31.1 2150.45    40.1 2148.84
      60 2146.36    67.1 2144.61    70.4 2142.86    76.8  2138.9    89.6  2133.6
    93.8 2132.24   105.4  2131.8   111.7 2132.18     121 2131.65   132.2  2132.1
   148.6 2129.34   161.5 2128.78   166.3 2128.98  168.22 2129.37   170.5 2129.91
   170.9 2130.24   177.1 2137.29   180.2 2140.48   187.3 2146.63   207.8  2162.2
   219.8  2168.6   231.9    2177   248.1 2186.98   255.9  2191.2   261.1 2194.78
#Mann= 3 ,-1,0
       0      .1       0   148.6    .045       0  168.22      .1       0
Bank Sta=148.6,168.22
XS Rating Curve= 0 ,0
Exp/Cntr(USF)=0,0
Exp/Cntr=0.3,0.1

Type RM Length L Ch R = 1 ,1347    ,46.7,46.7,46.7
XS GIS Cut Line= 5
2220160.98940599423999.5081296912220148.13727101424044.655373076
2220088.16064112424138.9043629152220069.04720961424159.665504033
2220054.87690694424237.437397747
#Sta/Elev= 30
       0 2165.18    10.1 2160.18    26.7 2153.49    47.6 2147.06    53.1 2144.05
      57 2141.06    66.5 2134.96    71.3 2132.58      76 2130.87    85.5 2128.91
    90.8 2128.69     114 2128.97   121.4  2128.1   142.4 2127.36   156.6 2128.84
   163.1 2128.27   167.2 2128.88   172.6 2128.87   180.1 2127.81   183.5 2128.67
   186.9 2131.08   192.6 2135.73   204.7 2143.93   209.6 2147.59   219.9 2154.48
   229.1 2159.97   240.5 2167.97   245.3 2170.28   253.5 2173.09   265.9 2182.09
#Mann= 3 ,0,0
       0      .1       0   156.6    .045       0   167.2      .1       0
#XS Ineff= 2 , 0
          107.64 2134.34
Permanent Ineff=
       F       F
Bank Sta=156.6,167.2
XS Rating Curve= 0 ,0
Exp/Cntr(USF)=0,0
Exp/Cntr=0.3,0.1

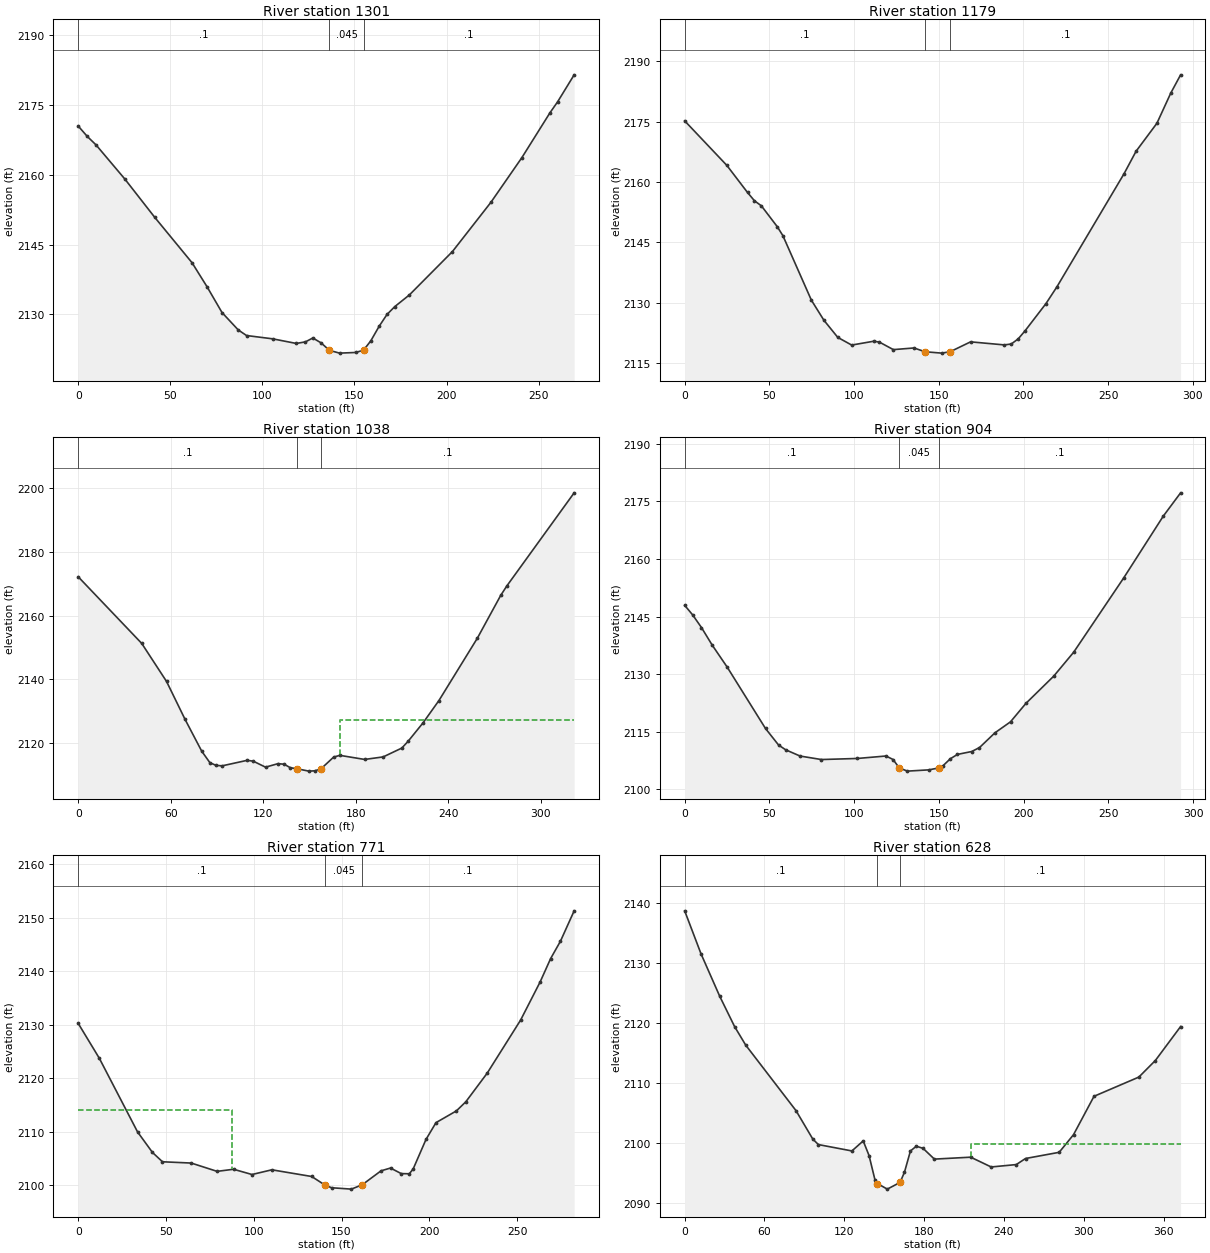
Type RM Length L Ch R = 1 ,1301    ,124.6,121.8,118.8
XS GIS Cut Line= 4
2220094.54674051423972.3104464192220080.55474613424051.071127706
  2220040.915163424127.9915840092220029.79828505424230.157376736
#Sta/Elev= 30
       0 2170.46     4.9 2168.24     9.7  2166.4    25.3 2159.09    41.5 2150.88
    61.8 2141.11    69.9 2135.98    78.1  2130.4    86.9 2126.67    91.4 2125.47
   105.6 2124.76   118.4 2123.77   123.4 2124.11   127.4 2124.94   131.9 2123.89
   136.4 2122.29   141.9 2121.69   150.7 2121.83  154.95 2122.33   158.9 2124.34
   163.4 2127.45   167.7 2130.01   171.9 2131.68   179.8 2134.18   203.2  2143.5
   224.1 2154.08   240.9 2163.67   256.2 2173.33   260.3 2175.65   269.3 2181.46
#Mann= 3 ,-1,0
       0      .1       0   136.4    .045       0  154.95      .1       0
Bank Sta=136.4,154.95
XS Rating Curve= 0 ,0
Exp/Cntr(USF)=0,0
Exp/Cntr=0.3,0.1

Type RM Length L Ch R = 1 ,1179    ,143.5,140.8,135.4
XS GIS Cut Line= 2
2219969.01445521423920.9035110552219906.12523011424206.839854528
#Sta/Elev= 30
       0 2175.17    24.9 2164.12    37.1  2157.4    41.2 2155.34    45.3 2154.08
    54.7 2148.89      58 2146.67    74.8 2130.68    82.2  2125.7    90.4 2121.44
    98.6 2119.54   111.7  2120.5     115 2120.27   123.2 2118.41   135.4 2118.82
   141.9 2117.88   151.8 2117.54   156.8  2117.9   168.8 2120.34   188.7 2119.58
   192.8  2119.8   196.9 2121.07     201  2123.1   213.3 2129.83   219.8 2134.01
   259.4 2162.05   266.5 2167.63   278.8 2174.57     287 2182.07   292.8 2186.59
#Mann= 3 ,-1,0
       0      .1       0   141.9    .045       0   156.8      .1       0
Bank Sta=141.9,156.8
XS Rating Curve= 0 ,0
Exp/Cntr(USF)=0,0
Exp/Cntr=0.3,0.1

Type RM Length L Ch R = 1 ,1038    ,135.5,133.8,129.7
XS GIS Cut Line= 2
2219790.50417663423904.1093133022219818.45494334424224.611438274
#Sta/Elev= 30
       0 2172.13    41.2 2151.27    57.3 2139.36    69.3 2127.49    80.1 2117.54
    85.4 2113.93    89.4 2113.08    93.4 2112.94   109.5 2114.65   113.5 2114.41
   121.5 2112.52   129.6 2113.62   133.6 2113.44   137.6 2112.34   141.6 2112.05
   149.6 2111.28   153.7 2111.38   157.7  2112.1   165.7 2115.68   169.7 2116.22
   185.8 2114.94   197.8 2115.73   209.9  2118.5   213.9 2120.57   223.7 2126.41
     234 2133.39   258.9  2152.9   274.1 2166.34   278.1 2169.31   321.7 2198.42
#Mann= 3 ,-1,0
       0      .1       0   141.6    .045       0   157.7      .1       0
#XS Ineff= 2 , 0
                          169.77         2127.32
Permanent Ineff=
       F       F
Bank Sta=141.6,157.7
XS Rating Curve= 0 ,0
Exp/Cntr(USF)=0,0
Exp/Cntr=0.3,0.1

Type RM Length L Ch R = 1 ,904     ,142,133.5,123.8
XS GIS Cut Line= 3
2219636.12082366423968.6993221342219690.62481875  424129.6957384
2219750.15995185424237.026682578
#Sta/Elev= 30
       0 2147.94     4.7 2145.45     9.9 2142.16    16.2  2137.6    25.1 2131.83
    47.7 2115.84    55.4 2111.54    59.6 2110.29    68.1 2108.66    80.7 2107.75
   101.9 2108.03   118.8 2108.67     123 2107.76   126.6 2105.59   131.4 2104.73
   144.1 2105.06   149.9 2105.56   152.5 2106.15   156.8 2107.96     161 2109.09
   169.4 2109.84     174 2110.87   183.1 2114.71   192.3 2117.58   201.4 2122.39
   217.8 2129.48   229.6 2135.73     259 2155.01   282.5 2171.21   292.7 2177.26
#Mann= 3 ,-1,0
       0      .1       0   126.6    .045       0   149.9      .1       0
Bank Sta=126.6,149.9
XS Rating Curve= 0 ,0
Exp/Cntr(USF)=0,0
Exp/Cntr=0.3,0.1

Type RM Length L Ch R = 1 ,771     ,136.2,142.6,149.1
XS GIS Cut Line= 2
2219467.19076624424082.4233486182219678.38116936424270.084796327
#Sta/Elev= 30
       0 2130.25      12 2123.75    33.8 2109.98    42.3 2106.14      48  2104.4
    64.4 2104.16    79.1 2102.61    88.5    2103      99 2102.02   110.3  2102.9
     133 2101.65   140.4 2100.08   144.3 2099.55   155.6 2099.29   161.8 2100.11
   172.5 2102.71   177.9 2103.23     184 2102.19   188.6 2102.16   190.8 2103.06
   198.1 2108.57   203.8 2111.71   215.4  2113.9   220.8 2115.61     233 2120.97
     252 2130.87   263.1 2137.98   269.1 2142.36   274.7 2145.61   282.5 2151.28
#Mann= 3 ,-1,0
       0      .1       0   140.4    .045       0   161.8      .1       0
#XS Ineff= 2 , 0
           87.71 2114.07
Permanent Ineff=
       F       F
Bank Sta=140.4,161.8
XS Rating Curve= 0 ,0
Exp/Cntr(USF)=0,0
Exp/Cntr=0.3,0.1

Type RM Length L Ch R = 1 ,628     ,138.7,134,130.2
XS GIS Cut Line= 5
2219406.85347647424093.4718057192219447.45491113424220.227504174
2219466.27021012424259.343520494 2219571.2397729424344.507505393
2219630.65650655424358.866549359
#Sta/Elev= 30
       0 2138.72    12.3 2131.55    26.3 2124.51    37.5 2119.45    45.9 2116.35
    83.7 2105.44    96.3 2100.71   100.5 2099.79   125.7 2098.73   134.2  2100.4
   138.6 2097.96     143 2093.95   144.9  2093.3   152.3 2092.37   161.92093.486
   165.2 2095.18   169.7 2098.72   174.1 2099.52   179.2 2099.16   187.7 2097.37
     215 2097.69   230.4 2096.06   249.3 2096.46   256.2 2097.47   281.5  2098.5
   292.3 2101.44   307.7 2107.83   341.4 2111.03   353.8 2113.79   372.8 2119.45
#Mann= 3 ,-1,0
       0      .1       0   144.9    .045       0   161.9      .1       0
#XS Ineff= 2 , 0
                          215.21         2099.88
Permanent Ineff=
       F       F
Bank Sta=144.9,161.9
XS Rating Curve= 0 ,0
Exp/Cntr(USF)=0,0
Exp/Cntr=0.3,0.1

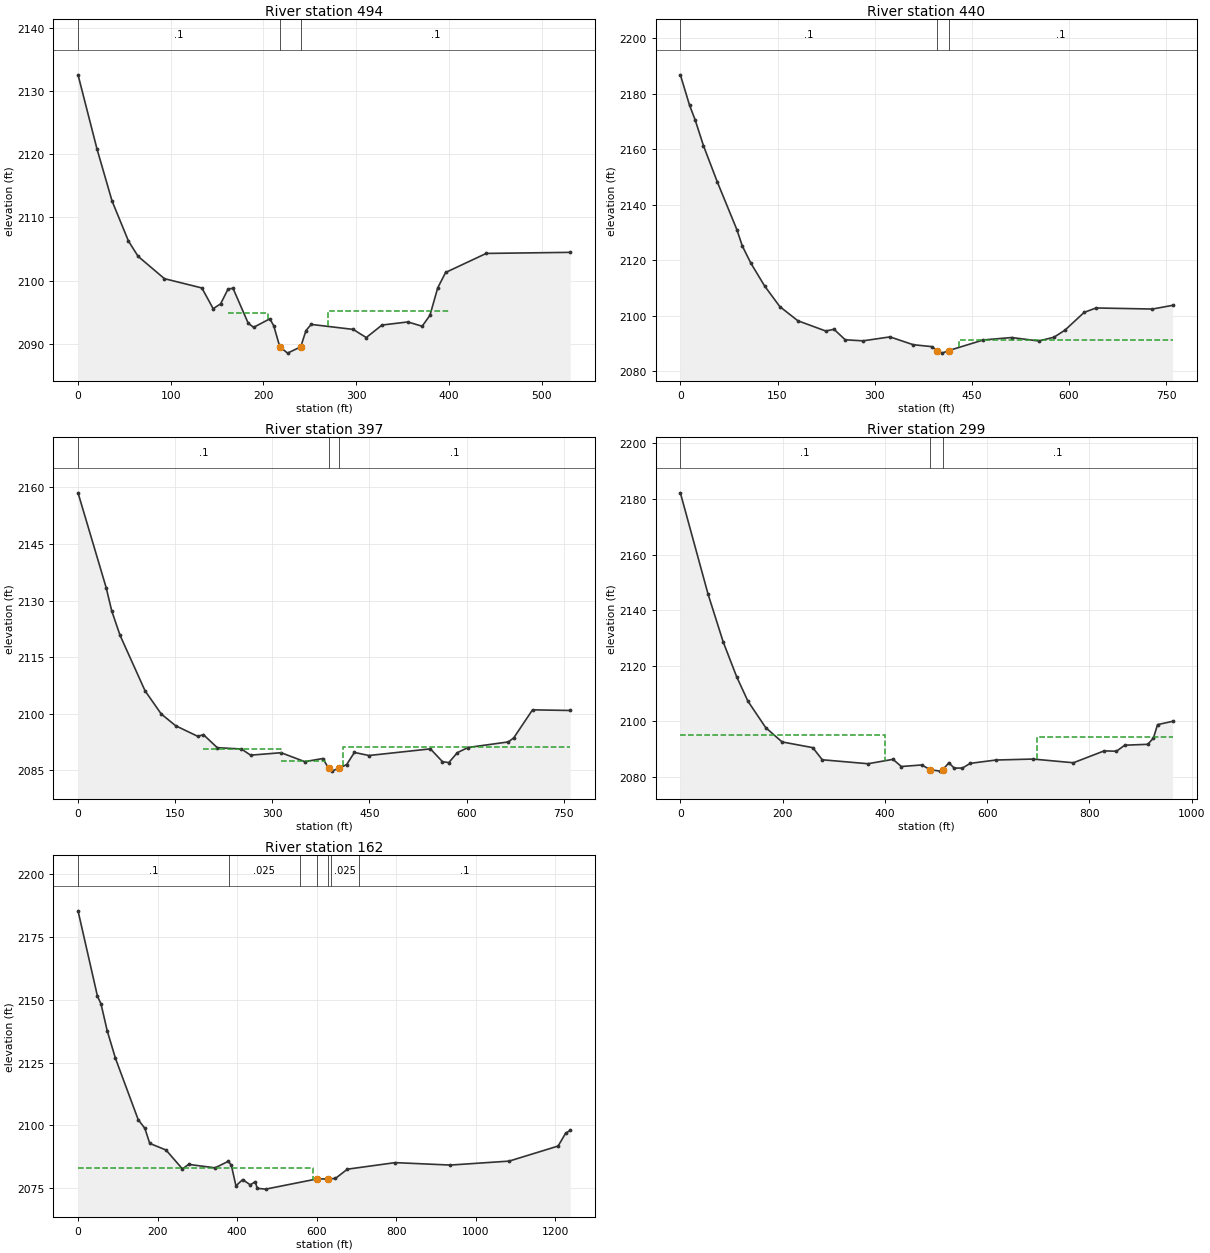
Type RM Length L Ch R = 1 ,494     ,56.8,53.8,51
BEGIN DESCRIPTION:
structure xs 4
END DESCRIPTION:
XS GIS Cut Line= 4
2219282.95575065424108.8629863742219305.70043287424269.583877128
2219428.68380641424400.9524806782219607.90929404424459.800390656
#Sta/Elev= 30
       0 2132.53    20.5 2120.79    36.7 2112.59    54.4 2106.26    64.8 2103.84
    93.2 2100.31   133.6 2098.84   145.8 2095.56   153.8 2096.33   161.9 2098.69
   167.2 2098.78   183.6 2093.26   189.4 2092.62   206.9 2093.96   211.1 2092.87
   217.6 2089.56     226 2088.54   240.2 2089.53   245.9 2092.11   251.5 2093.08
   296.8 2092.29   310.9    2091   327.9 2092.98   355.8 2093.47   371.2 2092.79
   379.6 2094.52     388 2098.86   396.5 2101.29   440.3  2104.3   530.9 2104.47
#Mann= 3 ,-1,0
       0      .1       0   217.6    .045       0   240.2      .1       0
#XS Ineff= 2 ,-1
  162.25  205.18 2094.93     270   400.9  2095.2
Permanent Ineff=
       F       F
Bank Sta=217.6,240.2
XS Rating Curve= 0 ,0
Exp/Cntr(USF)=0,0
Exp/Cntr=0.5,0.3

Type RM Length L Ch R = 1 ,440     ,43.3,43.3,43.3
BEGIN DESCRIPTION:
structure xs 3; 16.8 ft between structure and xs
END DESCRIPTION:
XS GIS Cut Line= 4
2219295.68887772424027.9092842662219199.41401459424276.360543934
2219453.04134217 424454.417280032219630.06286469424503.072318382
#Sta/Elev= 30
       0 2186.85    14.2 2175.89    22.8 2170.63    35.7  2161.3    57.1 2148.22
    87.2 2131.08    95.7 2125.14   108.8 2118.99   130.1 2110.74   153.6  2103.3
   181.5  2098.2   224.4 2094.52   237.3 2095.13   254.5 2091.35     282 2090.97
   323.6 2092.39   359.5 2089.58   388.2 2088.88   396.8  2087.4   404.2 2086.54
     414 2087.44   467.8 2091.29   511.5 2092.16   553.3 2090.92   576.9 2092.27
     594 2094.86   623.4 2101.22   641.8 2102.82   728.9 2102.43   759.9 2103.76
#Mann= 3 ,-1,0
       0      .1       0   396.8    .045       0     414      .1       0
#XS Ineff= 2 , 0
             380  2088.4   430.8          2091.3
Permanent Ineff=
       F       F
Bank Sta=396.8,414
XS Rating Curve= 0 ,0
Exp/Cntr(USF)=0,0
Exp/Cntr=0.5,0.3

Type RM Length L Ch R = 1 ,397     ,94.7,98,99.6
BEGIN DESCRIPTION:
structure xs 2; 17.6 ft between structure and xs
END DESCRIPTION:
XS GIS Cut Line= 4
2219273.94939249424064.6593664252219177.67452937424313.110626093
2219431.30185695424491.1673621892219608.32337947424539.822400541
#Sta/Elev= 30
       0 2158.56    43.5 2133.41      52  2127.3    64.9  2120.8   103.5  2106.1
   128.5 2099.96   150.7 2096.85     185 2094.03   193.6 2094.49     215 2091.03
   252.2 2090.69   266.5 2089.05   313.5  2089.7   350.1 2087.33     378 2088.16
   386.8 2085.61   391.8 2084.82   403.3 2085.65   414.7 2086.54   426.7 2089.77
   449.2 2088.96     544 2090.72   562.7 2087.33   572.5 2087.08   585.5  2089.7
   602.1 2091.08   664.4 2092.56   672.7 2093.63   701.7 2101.06   759.9 2100.89
#Mann= 3 ,-1,0
       0      .1       0   386.8    .045       0   403.3      .1       0
#XS Ineff= 4 ,-1
       0  192.45  2087.4  192.45  313.69 2090.57  313.69     381  2087.4
   409.3   759.9  2091.3
Permanent Ineff=
       F       F       F       F
Bank Sta=386.8,403.3
XS Rating Curve= 0 ,0
Exp/Cntr(USF)=0,0
Exp/Cntr=0.5,0.3

Type RM Length L Ch R = 1 ,299     ,137,137,137
BEGIN DESCRIPTION:
structure xs 1
END DESCRIPTION:
XS GIS Cut Line= 4
2219226.32956772424020.6627891922219091.75180207 424321.90994154
 2219330.8861395 424581.748550612219609.35859305424557.938638225
#Sta/Elev= 30
       0 2182.19    54.3  2145.7    83.8 2128.59   110.1 2116.09   132.2 2107.28
     167 2097.77   198.9 2092.65     259 2090.59   277.6 2086.23     367 2084.81
   415.9 2086.39   432.2 2083.81   472.3 2084.37   488.3 2082.68   508.1 2082.15
   513.8  2082.7   525.1 2085.19   535.5 2083.24   551.8 2083.26   566.8 2084.94
   617.1 2086.14   689.8 2086.49   768.7 2085.16   828.9 2089.43     853  2089.3
     869 2091.47   914.1 2091.79   925.2 2094.03   933.3 2098.86   962.6 2100.05
#Mann= 3 ,-1,0
       0      .1       0   488.3    .045       0   513.8      .1       0
#XS Ineff= 2 , 0
          401.13  2095.2  698.03         2094.41
Permanent Ineff=
       F       F
Bank Sta=488.3,513.8
XS Rating Curve= 0 ,0
Exp/Cntr(USF)=0,0
Exp/Cntr=0.3,0.1

Type RM Length L Ch R = 1 ,162     ,,,
XS GIS Cut Line= 4
2219033.77984148423957.5147606932218944.67900848424344.415484811
2219228.87619314424676.2739027782219621.78115603424584.854191356
#Sta/Elev= 30
       0 2185.36    48.9 2151.38    57.8 2148.33    73.5  2137.6    94.1  2126.7
   151.2 2102.34   168.1 2098.83   180.3 2092.87   221.3 2090.22   262.4 2082.72
     278 2084.52   344.5 2083.15   378.1 2085.77   385.5 2084.13     397 2075.98
   413.8 2078.47   433.1 2076.38   445.4 2077.62   450.7 2074.99   471.8 2074.68
   601.5 2078.76   627.22078.698   646.9 2078.91   677.1 2082.61   797.2 2085.22
   935.9 2084.25  1083.7 2085.82  1206.9 2091.81  1225.7  2096.9  1237.3 2098.04
#Mann= 7 ,-1,0
       0      .1       0     380    .025       0  557.03      .1       0
   601.5    .045       0   627.2      .1       0  637.03    .025       0
  707.03      .1       0
#XS Ineff= 2 , 0
          591.55 2082.93
Permanent Ineff=
       F       F
Bank Sta=601.5,627.2
XS Rating Curve= 0 ,0
Exp/Cntr(USF)=0,0
Exp/Cntr=0.3,0.1
LCMann Table=0

Chan Stop Cuts=-1
Use User Specified Reach Order=0
Composite Channel Slope=5